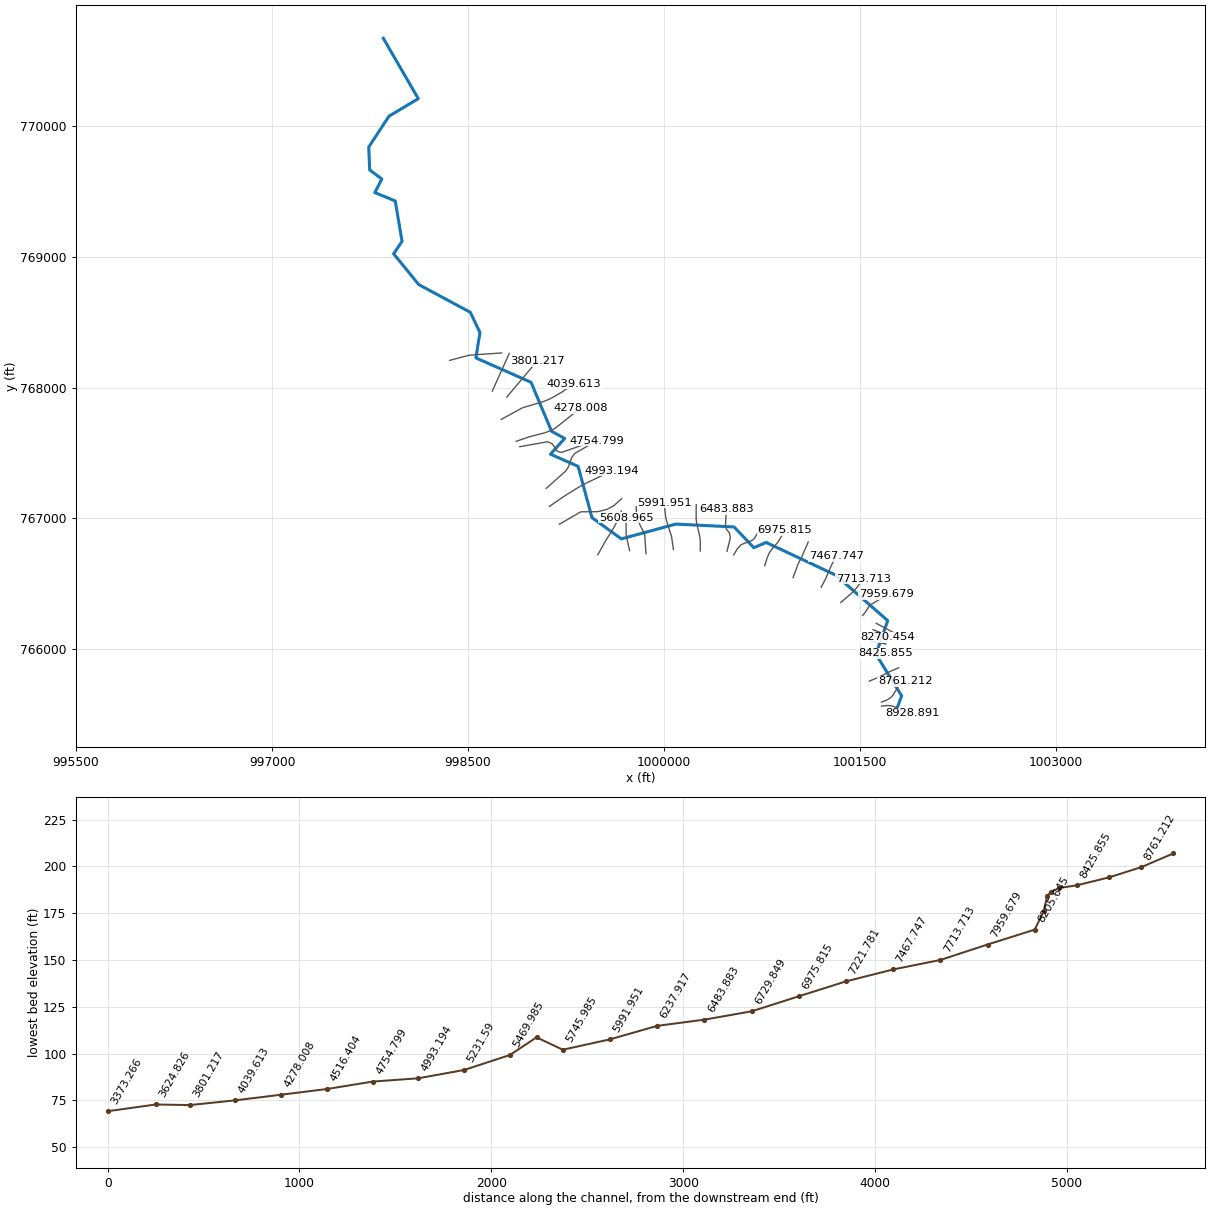
--- 160_ras.prj (project) ---

Proj Title=160
Current Plan=p01
Default Exp/Contr=0.3,0.1
English Units
Geom File=g01
Flow File=f01
Plan File=p01
Y Axis Title=Elevation
X Axis Title(PF)=Main Channel Distance
X Axis Title(XS)=Station
BEGIN DESCRIPTION:
RFD model 160 exported to HEC-RAS
END DESCRIPTION:

--- 160_ras.p01 (plan) ---

Plan Title=Plan 01
Program Version=4.10
Short Identifier=Plan 01
Geom File=g01
Flow File=f01
Subcritical Flow
Calc Critical at every XS
Secant Critical Depth

--- 160_ras.f01 (steady flow) ---

Flow Title=Flow 01
Program Version=5.01
Number of Profiles= 6
Profile Names=10yr,25yr,50yr,100yr,100plus,500yr
River Rch & RM=160,48,8928.891
   77.49  147.77  223.55  307.35  448.74 1044.76
River Rch & RM=160,48,7713.713
   78.54  149.79  226.63  311.59  454.92 1057.15
River Rch & RM=160,48,7467.747
   83.36  159.02  240.65  330.91  483.13 1113.44
River Rch & RM=160,48,7221.781
   95.85  182.98  277.07   381.1  556.41 1257.64
River Rch & RM=160,48,6975.815
  102.86  196.42  297.51  409.28  597.56 1337.48
River Rch & RM=160,48,6729.849
  103.65  197.94  299.82  412.47  602.21 1346.49
River Rch & RM=160,48,6483.883
  110.28   210.7  319.27  439.34  641.43 1422.11
River Rch & RM=160,48,6237.917
  119.72  228.87  346.94  477.54  697.21  1528.4
River Rch & RM=160,48,5991.951
  122.56  234.34  355.29  489.08  714.05 1560.36
River Rch & RM=160,48,5745.985
  125.96  240.89  365.27  502.87  734.19 1598.37
River Rch & RM=160,48,5608.965
  126.33  241.61  366.38  504.39  736.42 1602.57
River Rch & RM=160,48,5469.985
  128.78  246.33  373.56  514.32   750.9 1629.78
River Rch & RM=160,48, 5231.59
  192.82  369.63  561.58  773.98 1130.01 2319.28
River Rch & RM=160,48,4993.194
  197.57  378.83  575.66  793.47 1158.47 2369.91
River Rch & RM=160,48,4754.799
  197.91  379.49  576.66  794.86 1160.49 2373.51
River Rch & RM=160,48,4516.404
  203.64  390.58  593.64  818.38 1194.83 2434.39
River Rch & RM=160,48,4278.008
  204.48  392.21  596.13  821.83 1199.87  2443.3
River Rch & RM=160,48,4039.613
  230.95   443.5  674.66  930.64 1358.74 2721.87
River Rch & RM=160,48,3801.217
  234.19  449.78  684.29  944.01 1378.26 2755.89
River Rch & RM=160,48,3624.826
  238.47  458.13  697.14  961.89 1404.36 2801.56
River Rch & RM=160,48,3373.266
  242.95  466.84  710.51  980.45 1431.46 2848.62
River Rch & RM=160,48,3179.695
  244.67  470.21   715.7  987.67    1442 2867.02
River Rch & RM=160,48, 3003.45
  246.08  472.96  719.93  993.57 1450.61 2882.04
River Rch & RM=160,48,2827.205
  250.77  482.11  734.03 1013.19 1479.26  2931.9
River Rch & RM=160,48,2650.961
  252.63  485.76  739.64 1021.01 1490.68 2951.75
River Rch & RM=160,48,2506.584
   255.9  492.13  749.46 1034.68 1510.63 2986.36
River Rch & RM=160,48,2374.961
  256.67  493.65  751.79 1037.93 1515.37 2994.57
River Rch & RM=160,48,2162.694
  257.91  496.07  755.52 1043.12 1522.95  3007.7
River Rch & RM=160,48,1950.427
  259.61  499.39  760.63 1050.24 1533.35 3025.72
River Rch & RM=160,48, 1738.16
  260.22  500.59  762.48 1052.82 1537.12 3032.26
River Rch & RM=160,48,1569.004
  265.46  510.83  778.25 1074.78 1569.19 3087.64
River Rch & RM=160,48,1416.989
  268.17  516.16   786.5  1086.3    1586 3116.79
River Rch & RM=160,48,1189.961
  269.51  518.79  790.57    1092 1594.32 3131.33
River Rch & RM=160,48,962.9321
  271.28  522.29  795.99  1099.6 1605.42 3150.68
River Rch & RM=160,48,735.9034
  272.91   525.5  800.97 1106.56 1615.58 3168.37
River Rch & RM=160,48,508.8748
  313.96  605.85  924.86 1279.23 1867.68 3597.45
River Rch & RM=160,48,281.8461
  314.82  607.56  927.49 1282.92 1873.07 3606.62
River Rch & RM=160,48, 99.5794
  315.54  608.97  929.69    1286 1877.55 3614.25
River Rch & RM=160,48,       0
  316.54  610.95  932.76 1290.29 1883.82 3624.92
Boundary for River Rch & Prof#=160,48,1
Up Type= 0
Dn Type= 2
Boundary for River Rch & Prof#=160,48,2
Up Type= 0
Dn Type= 2
Boundary for River Rch & Prof#=160,48,2
Up Type= 0
Dn Type= 2
Boundary for River Rch & Prof#=160,48,2
Up Type= 0
Dn Type= 2
Boundary for River Rch & Prof#=160,48,2
Up Type= 0
Dn Type= 2
Boundary for River Rch & Prof#=160,48,2
Up Type= 0
Dn Type= 2

--- 160_ras.g01 (geometry) ---

Geom Title=160
Program Version=4.10

River Reach=160,48
Reach XY= 30
1001784.85081196765548.1898529811001820.04744911765642.699341753
1001622.97470536765960.7399726551001713.28076522766217.805978938
1001314.84326524766565.7226455861000783.07243191766815.201812276
1000688.80159854766775.0976455891000537.23909856766933.951812247
1000090.95398973766955.815646489999674.218265251766842.805978922
999449.218265208767005.305978934999343.489098565767396.972645585
999131.560101364767490.252586356999240.364098534767610.514312244
999140.122357503767665.256830512998983.072431924768039.680978934
998560.728341192768226.309827995998591.926598551768419.889312251
998517.968265237768575.097645592998123.697431895768786.555978941
997930.989098535 769022.14625668997995.572431907769117.285145572
997943.489098564769426.312923363997787.239098552769490.201812245
997840.711320789769594.368478931997747.655765237769663.118478924
997740.610640958769838.566887778997895.572431865770074.229590027
998119.877987432770208.257367802997852.283351098770669.474495905

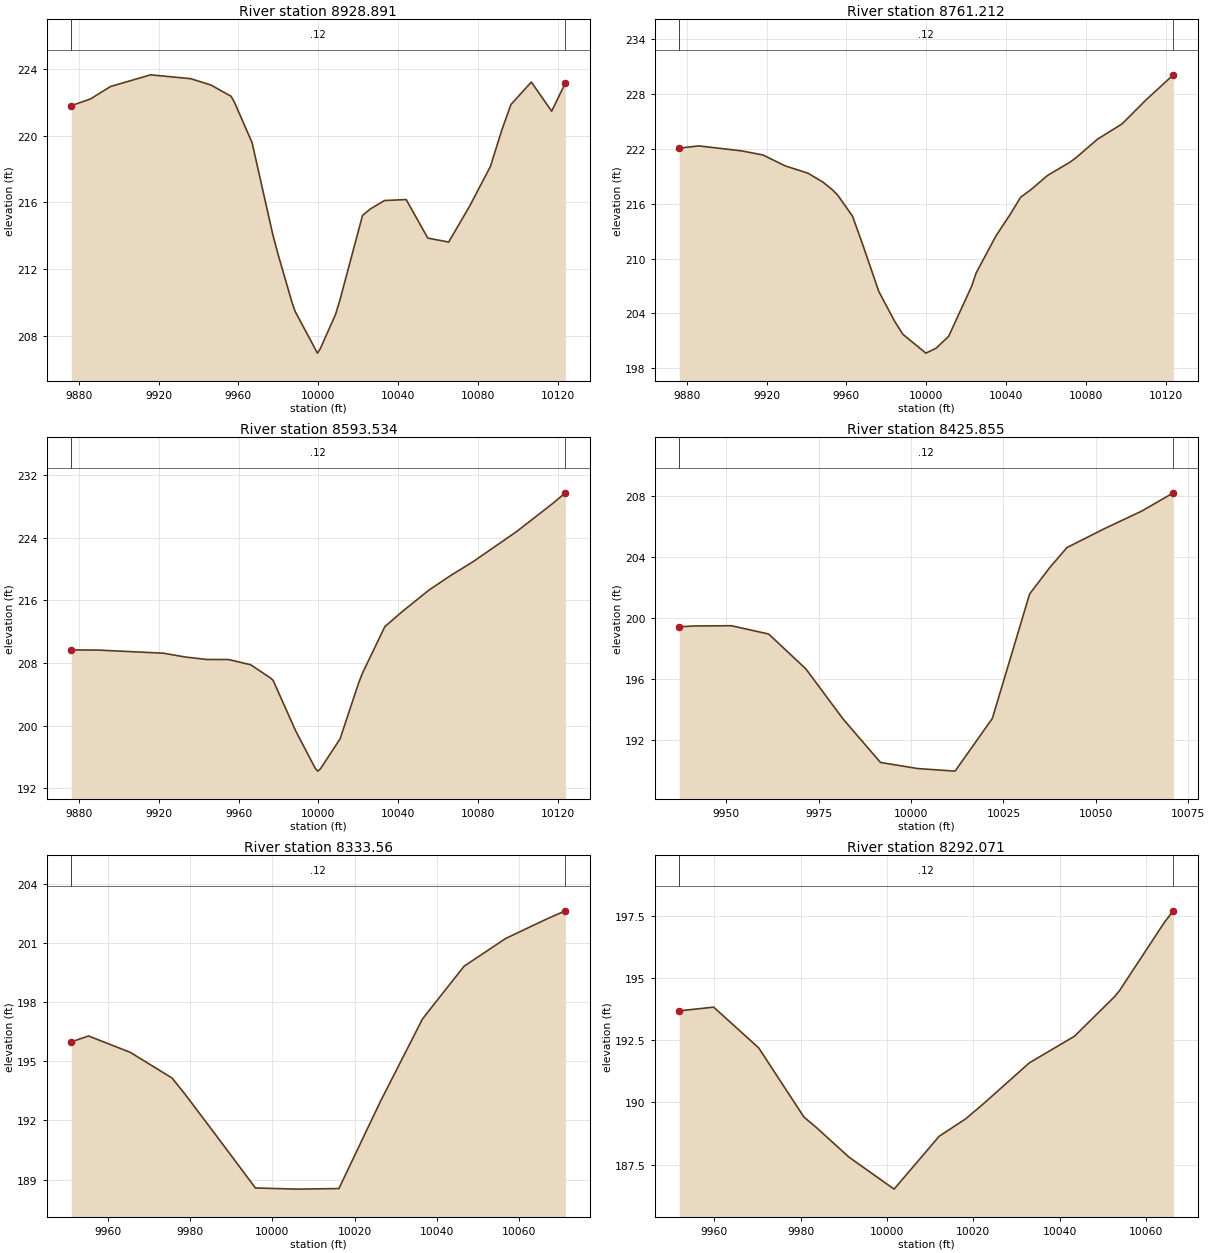
Type RM Length L Ch R = 1 ,8928.891,167.678600,167.678600,167.678600
XS GIS Cut Line= 6
1001665.43610762765564.0604694741001709.07729955765568.924081531
1001743.27174507765566.1212526371001767.59990819765558.053337308
1001834.03053096765526.0339092741001901.72580888765508.642090298
#Sta/Elev= 30
9876.184221.78399885.807222.18359895.869222.93019915.993 223.6289936.024223.3982
9946.101223.02419956.292222.34779958.033221.97859966.827219.57489977.363214.0077
9980.102212.79169986.891210.00719988.387209.4895  9999.6206.9894   10001207.2484
10008.67209.304210010.92 210.18810022.21215.224910026.16 215.61110033.23216.1129
10044.09216.170610054.91 213.86710065.38213.629910075.84215.7674 10086.3218.1482
10092.05220.3396 10096.6 221.85210106.81223.196310117.01221.453510123.88223.1443
#Mann= 3 , 0 , 0
9876.184    0.12       09876.184    0.12       010123.88    0.12       0
#XS Ineff= 2 , 0
       0                               0
Bank Sta=9876.184,10123.88
Exp/Cntr=0.3,0.1

Type RM Length L Ch R = 1 ,8761.212,167.678600,167.678600,167.678600
XS GIS Cut Line= 6
1001665.83851911 765595.058456481001708.81510677765611.496636271
1001736.97106848765629.4142968181001753.22568803 765648.30420981
1001791.03404353765709.197992044 1001846.0465835765754.332576477
#Sta/Elev= 30
9876.225222.09179886.034222.33099907.447221.78779918.154221.33989929.307 220.144
9940.736219.34599948.386218.34499953.223217.48179955.696 216.9229963.065214.6351
9968.005211.62699976.257206.37929984.186203.11989988.333201.69499999.798199.6439
10004.88 200.17210011.21201.4827 10022.7206.944910024.96208.403910034.93212.4863
10042.09214.843810047.25216.702310052.42217.539110060.75219.094610071.89220.5333
 10075.1221.047410085.83223.071710098.09224.736910110.31227.4108 10123.8230.1128
#Mann= 3 , 0 , 0
9876.225    0.12       09876.225    0.12       0 10123.8    0.12       0
#XS Ineff= 2 , 0
       0                               0
Bank Sta=9876.225,10123.8
Exp/Cntr=0.3,0.1

Type RM Length L Ch R = 1 ,8593.534,167.678600,167.678600,167.678600
XS GIS Cut Line= 6
1001572.37791216 765754.906301441001644.52585676765785.417951316
1001684.41353515765805.3001082021001686.15993055765806.274840519
1001729.85711769765828.5099076281001797.81441693 765857.45694588
#Sta/Elev= 25
9876.097209.59729878.944209.65719889.802209.63789922.374209.24369933.232208.7564
9944.089208.43959954.962208.43849966.135207.76299975.911206.09219977.308205.7943
9988.482199.41899998.327194.61359999.672194.1967   10001194.464910010.92198.3169
10020.24205.468210022.14206.695910033.36212.633210042.29 214.59410055.62217.3184
10066.49219.174310077.36220.8752 10099.1224.696710117.63228.359810123.89229.7022
#Mann= 3 , 0 , 0
9876.097    0.12       09876.097    0.12       010123.89    0.12       0
#XS Ineff= 2 , 0
       0                               0
Bank Sta=9876.097,10123.89
Exp/Cntr=0.3,0.1

Type RM Length L Ch R = 1 ,8425.855,92.295300,92.295300,92.295300
XS GIS Cut Line= 2
1001561.03177911765951.7045908871001693.53545162   765969.441303
#Sta/Elev= 17
9937.291199.41129941.294199.46089951.384199.47919961.473198.93699962.129198.7902
9971.562196.64659981.651193.3577 9991.74190.516910001.83190.116910011.92189.9482
10022.01193.4019 10032.1201.5635 10037.5203.278110042.19204.600110052.28205.8341
10062.36206.983210070.98208.1889
#Mann= 3 , 0 , 0
9937.291    0.12       09937.291    0.12       010070.98    0.12       0
#XS Ineff= 2 , 0
       0                               0
Bank Sta=9937.291,10070.98
Exp/Cntr=0.3,0.1

Type RM Length L Ch R = 1 , 8333.56,41.488900,41.488900,41.488900
XS GIS Cut Line= 2
1001580.85516319766059.6898673471001699.27379969766039.344815254
#Sta/Elev= 16
9951.118  195.999955.324196.2906 9965.47195.45949975.617194.15839978.815193.3283
9985.763191.4034 9995.91188.573710006.06188.5152 10016.2188.543910026.35192.9889
 10036.5197.143110037.87197.514710046.64199.831610056.79 201.24510066.94202.2489
10071.27202.6435
#Mann= 3 , 0 , 0
9951.118    0.12       09951.118    0.12       010071.27    0.12       0
#XS Ineff= 2 , 0
       0                               0
Bank Sta=9951.118,10071.27
Exp/Cntr=0.3,0.1

Type RM Length L Ch R = 1 ,8292.071,21.617500,21.617500,21.617500
XS GIS Cut Line= 2
1001597.35990039766104.218628064 1001706.9194963766071.062434569
#Sta/Elev= 16
9951.892193.68619959.874193.83529970.322192.1918 9980.77189.41639983.718188.9825
9991.218   187.810001.67186.512110012.11188.639310018.24189.339110022.56189.9757
10033.01191.595210043.46192.664410052.76194.260310053.91194.505210064.35 197.264
10066.36197.7109
#Mann= 3 , 0 , 0
9951.892    0.12       09951.892    0.12       010066.36    0.12       0
#XS Ineff= 2 , 0
       0                               0
Bank Sta=9951.892,10066.36
Exp/Cntr=0.3,0.1

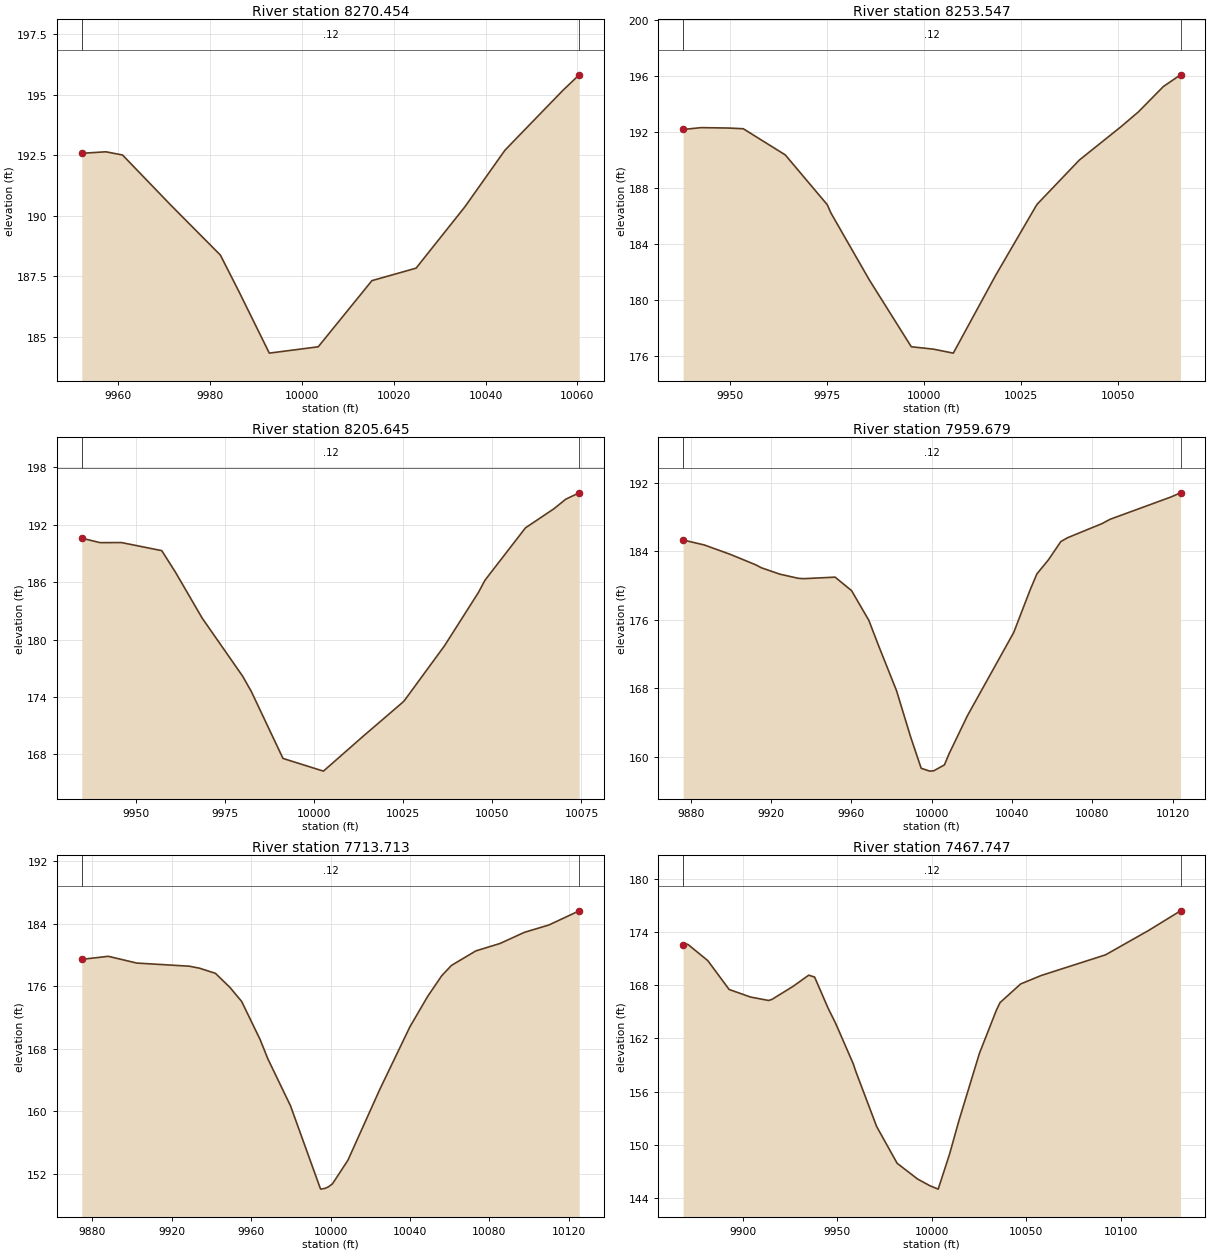
Type RM Length L Ch R = 1 ,8270.454,16.906400,16.906400,16.906400
XS GIS Cut Line= 2
1001606.67468381766126.8125224861001708.33334738766089.414775789
#Sta/Elev= 16
9952.073192.57699957.322192.63869960.943192.50659971.599190.41049982.254188.3757
9986.287186.87269992.909184.328510003.56184.589710014.22187.079310015.25187.3206
10024.87187.835710035.53190.375610044.21192.700710046.19193.090810056.84195.1739
10060.39195.8152
#Mann= 3 , 0 , 0
9952.073    0.12       09952.073    0.12       010060.39    0.12       0
#XS Ineff= 2 , 0
       0                               0
Bank Sta=9952.073,10060.39
Exp/Cntr=0.3,0.1

Type RM Length L Ch R = 1 ,8253.547,47.902500,47.902500,47.902500
XS GIS Cut Line= 2
1001600.67854726766149.4167637081001719.09718373766100.901639506
#Sta/Elev= 19
9938.067 192.2069942.737192.33619949.717192.30679953.544192.2568 9964.35190.3866
9975.157186.82599976.095186.23469985.964181.4558 9996.77176.675410002.47176.5036
10007.58176.219810018.38181.734510028.85186.731710029.19186.8732   10040190.0179
 10050.8192.419510055.23193.469510061.61195.270710066.04196.1095
#Mann= 3 , 0 , 0
9938.067    0.12       09938.067    0.12       010066.04    0.12       0
#XS Ineff= 2 , 0
       0                               0
Bank Sta=9938.067,10066.04
Exp/Cntr=0.3,0.1

Type RM Length L Ch R = 1 ,8205.645,245.965900,245.965900,245.965900
XS GIS Cut Line= 2
1001625.19694337766197.4102199081001748.31059188 766131.68005164
#Sta/Elev= 21
9934.794190.60219939.912190.13589945.907190.14549957.243189.29939961.144187.0039
9968.579182.24369979.915176.18429982.377174.56469991.251167.578910002.59166.2526
10003.61166.584610013.92169.956510024.84173.447610025.26 173.60110036.59179.3677
10046.07184.917310047.93186.211910059.27 191.67710067.31193.6875 10070.6  194.68
10074.36195.3428
#Mann= 3 , 0 , 0
9934.794    0.12       09934.794    0.12       010074.36    0.12       0
#XS Ineff= 2 , 0
       0                               0
Bank Sta=9934.794,10074.36
Exp/Cntr=0.3,0.1

Type RM Length L Ch R = 1 ,7959.679,245.966000,245.966000,245.966000
XS GIS Cut Line= 6
1001520.77027921766256.8167728111001543.47988235 766284.89715104
1001570.63061595 766326.800437761001581.51780458766338.539224691
1001650.01177261766379.5256419791001703.55759692766417.719288012
#Sta/Elev= 30
9876.175185.30749886.699184.7284 9899.56183.63799912.411182.39969915.084 182.067
9924.327181.31559933.474180.83279936.243  180.799951.864180.96719960.074179.3866
9968.645175.92739973.402173.02479982.489167.67699989.446162.31629994.722158.6372
    9999158.3036   10001158.346710006.28159.028310008.66160.355510017.79164.7972
10040.82174.508510048.99179.484410052.34181.344310058.11182.995510064.24185.1151
10067.54185.564110084.76187.221410088.81187.7273 10119.2190.339510123.88190.8181
#Mann= 3 , 0 , 0
9876.175    0.12       09876.175    0.12       010123.88    0.12       0
#XS Ineff= 2 , 0
       0                               0
Bank Sta=9876.175,10123.88
Exp/Cntr=0.3,0.1

Type RM Length L Ch R = 1 ,7713.713,245.965900,245.965900,245.965900
XS GIS Cut Line= 6
1001354.04642003766356.2812367481001446.84012812766436.378582376
1001448.00895915766437.6525410241001449.32596837766439.157694412
 1001480.8526457766475.1923480131001525.17476479766537.448063457
#Sta/Elev= 27
9874.689179.42219888.033179.81359902.369178.9502 9928.79178.55049933.945178.2961
    9942177.64129949.249175.8622 9955.21174.05419964.553 169.169 9968.42166.7167
9979.857160.7019 9994.84150.16479995.161150.05599997.271150.1533    9999150.3555
   10001150.736710008.76153.7426 10024.8162.784510039.99170.793610048.88174.6568
10056.03177.330110060.92178.645610073.19180.499810085.47181.458910097.74182.8821
10110.02183.8135 10125.3185.6259
#Mann= 3 , 0 , 0
9874.689    0.12       09874.689    0.12       0 10125.3    0.12       0
#XS Ineff= 2 , 0
       0                               0
Bank Sta=9874.689,10125.3
Exp/Cntr=0.3,0.1

Type RM Length L Ch R = 1 ,7467.747,245.966000,245.966000,245.966000
XS GIS Cut Line= 6
1001203.79003307766473.4785486461001239.81935279766541.321902188
1001260.83496596766590.9907287251001261.61526403766592.832232166
1001285.31572549766646.7027097571001319.49423703766709.962595879
#Sta/Elev= 30
9868.251172.59129869.974172.65599870.831172.60429881.297 170.7869892.619167.5252
9903.942166.67069913.472166.28339915.265166.39769926.587167.88899934.793169.1406
 9937.91168.92379945.068165.40469949.062163.69419958.363159.1409 9959.92158.1619
9970.778152.04989981.637147.90029992.495146.1191    9999145.368710003.37144.9849
10009.41148.944310014.29152.672610025.22160.316710034.24165.205310036.14166.0435
10047.07  168.1510057.99169.105410092.02171.432810114.75 174.17410131.76 176.402
#Mann= 3 , 0 , 0
9868.251    0.12       09868.251    0.12       010131.76    0.12       0
#XS Ineff= 2 , 0
       0                               0
Bank Sta=9868.251,10131.76
Exp/Cntr=0.3,0.1

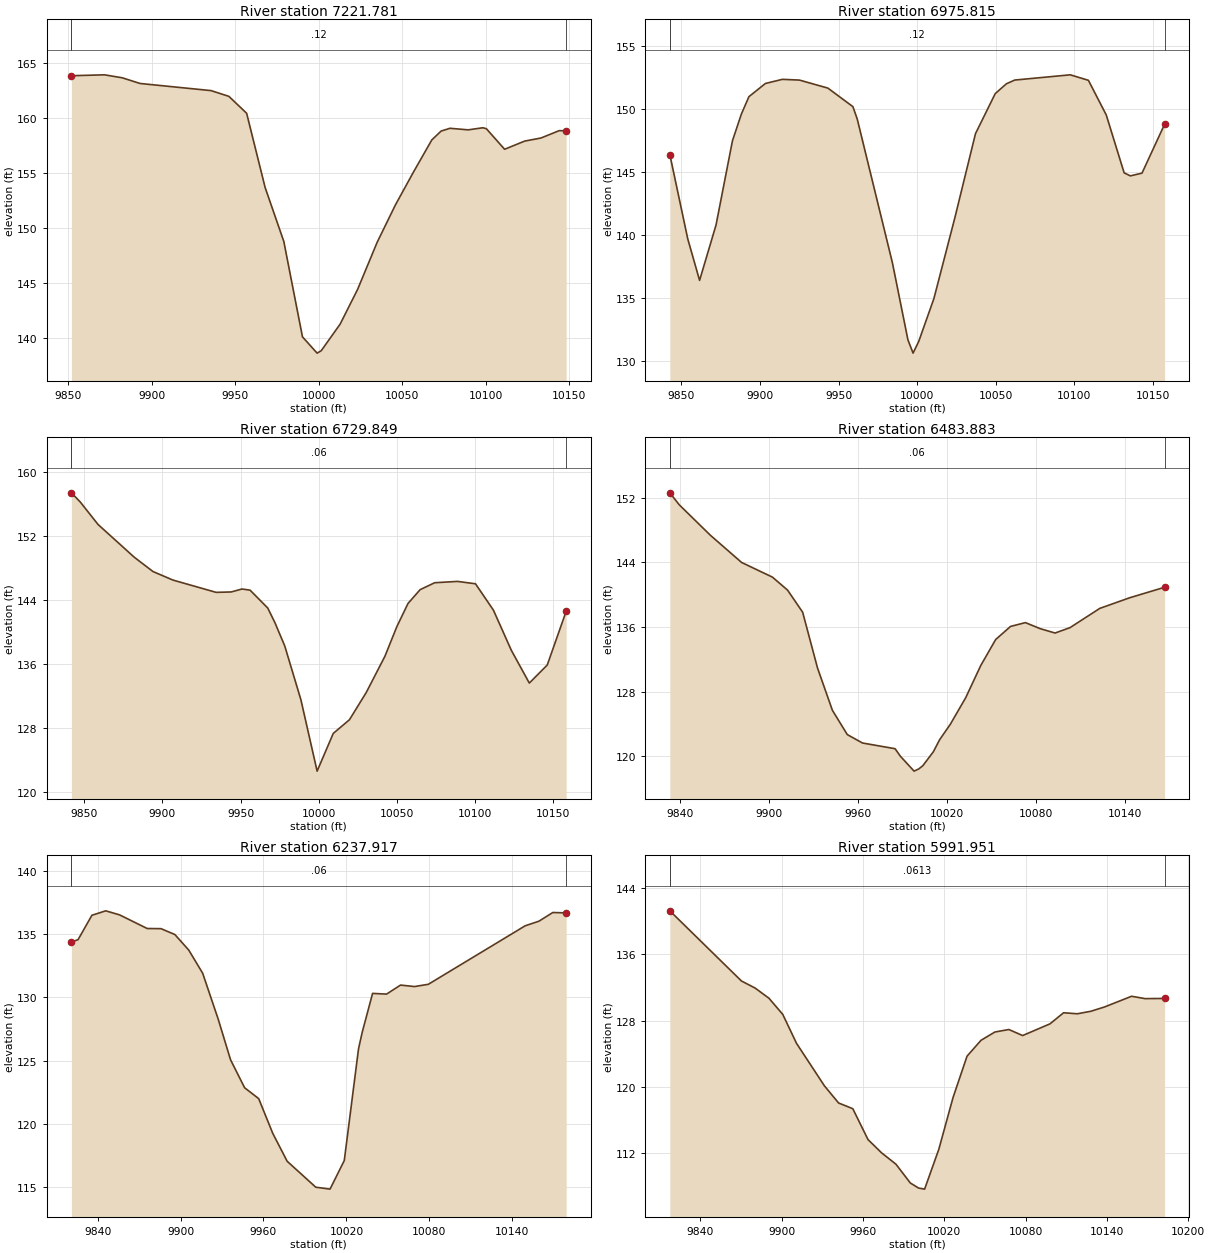
Type RM Length L Ch R = 1 ,7221.781,245.965900,245.965900,245.965900
XS GIS Cut Line= 6
1000988.97347283766546.3504590931001025.52678089766646.660059334
1001043.61156626766682.8392603011001044.62161207766684.565472185
1001055.26766464766704.7997601841001104.90950518766818.824815009
#Sta/Elev= 28
 9851.79163.8722 9871.64163.95379882.283163.68179892.926163.16669935.499162.5157
9946.142161.99349956.786160.45249967.876 153.6879979.056148.78359990.236140.0974
    9999138.616310001.49138.838710012.79141.254310023.29144.424910034.99148.7084
 10045.9152.1023 10056.8155.116310067.71158.0233 10073.3 158.83210078.62159.0863
10089.52 158.94410098.35159.134910100.43159.046610111.34157.1767 10123.4157.9218
10133.15158.201810144.05158.870310148.23158.8581
#Mann= 3 , 0 , 0
 9851.79    0.12       0 9851.79    0.12       010148.23    0.12       0
#XS Ineff= 2 , 0
       09880.935                       0
Bank Sta=9851.79,10148.23
Exp/Cntr=0.3,0.1

Type RM Length L Ch R = 1 ,6975.815,245.965900,245.965900,245.965900
XS GIS Cut Line= 6
1000771.65880053766636.9134013411000789.86922841766696.299074694
1000805.72882357 766733.284381061000820.21202538766755.155131689
 1000876.7928471766823.0553511071000925.31250566766907.661839998
#Sta/Elev= 30
9842.734146.39519854.131139.70619861.652136.41349872.112140.80529882.571147.4985
9888.241149.61289893.031150.98869903.491152.03249914.317152.36259925.197152.3012
9943.242151.66489959.143150.19459961.883149.21969984.255137.8113 9994.13131.6948
9997.391130.6424   10001131.573310010.65 134.97510023.94141.370910037.08148.0526
10049.63151.229510056.78152.012710062.04152.305310097.36152.719710108.88152.2843
10120.24149.532310131.59144.944910135.56 144.70410142.95144.919910157.32148.7985
#Mann= 3 , 0 , 0
9842.734    0.12       09842.734    0.12       010157.32    0.12       0
#XS Ineff= 2 , 0
       09935.686                       0
Bank Sta=9842.734,10157.32
Exp/Cntr=0.3,0.1

Type RM Length L Ch R = 1 ,6729.849,245.966000,245.966000,245.966000
XS GIS Cut Line= 6
1000534.30264983766720.0190384921000561.26929242 766765.89729804
1000591.92220823766799.0243082051000671.28614431766829.538538148
1000690.84126631766842.9414841561000746.72535514766935.529247392
#Sta/Elev= 30
9841.742157.41879847.414 156.2719858.801153.45659881.966149.36319893.929147.5751
9906.772 146.5029934.305144.9716 9943.96145.02049950.906  145.399956.034145.2452
9967.312143.01839971.971141.16159978.221138.25889988.564131.52159998.907122.6136
10009.23127.329310019.59129.040110030.32132.442710042.28136.979610049.93140.6945
10057.04143.578910064.81145.311410074.11146.174910088.72146.3409 10100.2146.0442
10111.68142.747310123.16 137.71510134.64133.627210146.12135.887710158.21142.6077
#Mann= 3 , 0 , 0
9841.742    0.06       09841.742    0.06       010158.21    0.06       0
#XS Ineff= 2 , 0
       0                               0
Bank Sta=9841.742,10158.21
Exp/Cntr=0.3,0.1

Type RM Length L Ch R = 1 ,6483.883,245.965900,245.965900,245.965900
XS GIS Cut Line= 6
1000483.40565944766748.9154604621000508.73965514766852.250640406
1000502.36409505766885.4149657341000477.91072164766918.325662528
1000471.38530881   766939.7498931000477.43109855767068.531996591
#Sta/Elev= 30
9833.199152.60659839.591151.11929860.599147.34769881.608143.98989902.388142.1768
9912.595140.5696 9922.76137.83779932.785130.93889942.815125.70339952.863122.6978
9963.089121.65779985.088120.95059988.589120.03459997.879118.1771   10001118.4415
10003.78118.8452 10010.9 120.57410015.15122.070710022.37123.983310032.79127.2897
10042.91131.261210052.93134.461310062.95136.079110072.95136.549610082.96135.8008
10092.98135.261710103.02135.927410123.11138.308510143.19139.619710166.82140.9225
#Mann= 3 , 0 , 0
9833.199    0.06       09833.199    0.06       010166.82    0.06       0
#XS Ineff= 2 , 0
       0                               0
Bank Sta=9833.199,10166.82
Exp/Cntr=0.3,0.1

Type RM Length L Ch R = 1 ,6237.917,245.966000,245.966000,245.966000
XS GIS Cut Line= 6
1000278.40821105766750.183929676 1000279.1879496766812.792455655
1000275.65397989766856.1837775041000251.95750048766957.618833825
1000246.82421411766992.038522694 1000247.3587039767104.650003464
#Sta/Elev= 30
9821.072134.36419825.889134.5523 9835.89136.4778 9845.89136.83029855.891136.5123
9875.893135.43419885.901135.42229895.934134.95689905.967133.7293    9916131.9098
9927.221128.29129936.188125.0707 9946.36122.86549956.531122.0073 9966.78119.2515
9977.125117.06479997.815115.015910008.14114.864110018.44117.120910028.75125.9431
10031.44127.255710038.91130.312910049.02 130.25710059.13130.968910069.21 130.853
10079.21131.029710149.26 135.64710159.27136.013710169.27 136.69710178.93136.6669
#Mann= 3 , 0 , 0
9821.072    0.06       09821.072    0.06       010178.93    0.06       0
#XS Ineff= 2 , 0
       0                               0
Bank Sta=9821.072,10178.93
Exp/Cntr=0.3,0.1

Type RM Length L Ch R = 1 ,5991.951,245.965900,245.965900,245.965900
XS GIS Cut Line= 6
1000072.89438956766762.501661381 1000057.9070821766864.004472937
1000024.21675757766967.1491207691000013.95191174767009.561622976
1000007.48021258767063.3397955541000005.79350086767119.351681152
#Sta/Elev= 30
9817.455 141.2429870.289132.77479880.403131.9192 9890.59130.69079900.777128.7449
9910.964125.23939931.585120.10329941.996118.04679952.455117.3601 9963.69113.6315
9973.686112.03189984.302110.65989994.917108.3902   10001107.779810005.45 107.651
10015.94112.463710026.43118.711310036.76123.699310047.05125.612810057.33126.6166
10067.62126.916410077.79126.186410097.94127.598810108.01128.939810118.08128.8148
10128.14129.119910138.15129.634510158.16130.929810168.16130.643810182.52130.6665
#Mann= 3 , 0 , 0
9817.455  0.0613       09817.455  0.0613       010182.52  0.0613       0
#XS Ineff= 2 , 0
       0                               0
Bank Sta=9817.455,10182.52
Exp/Cntr=0.3,0.1

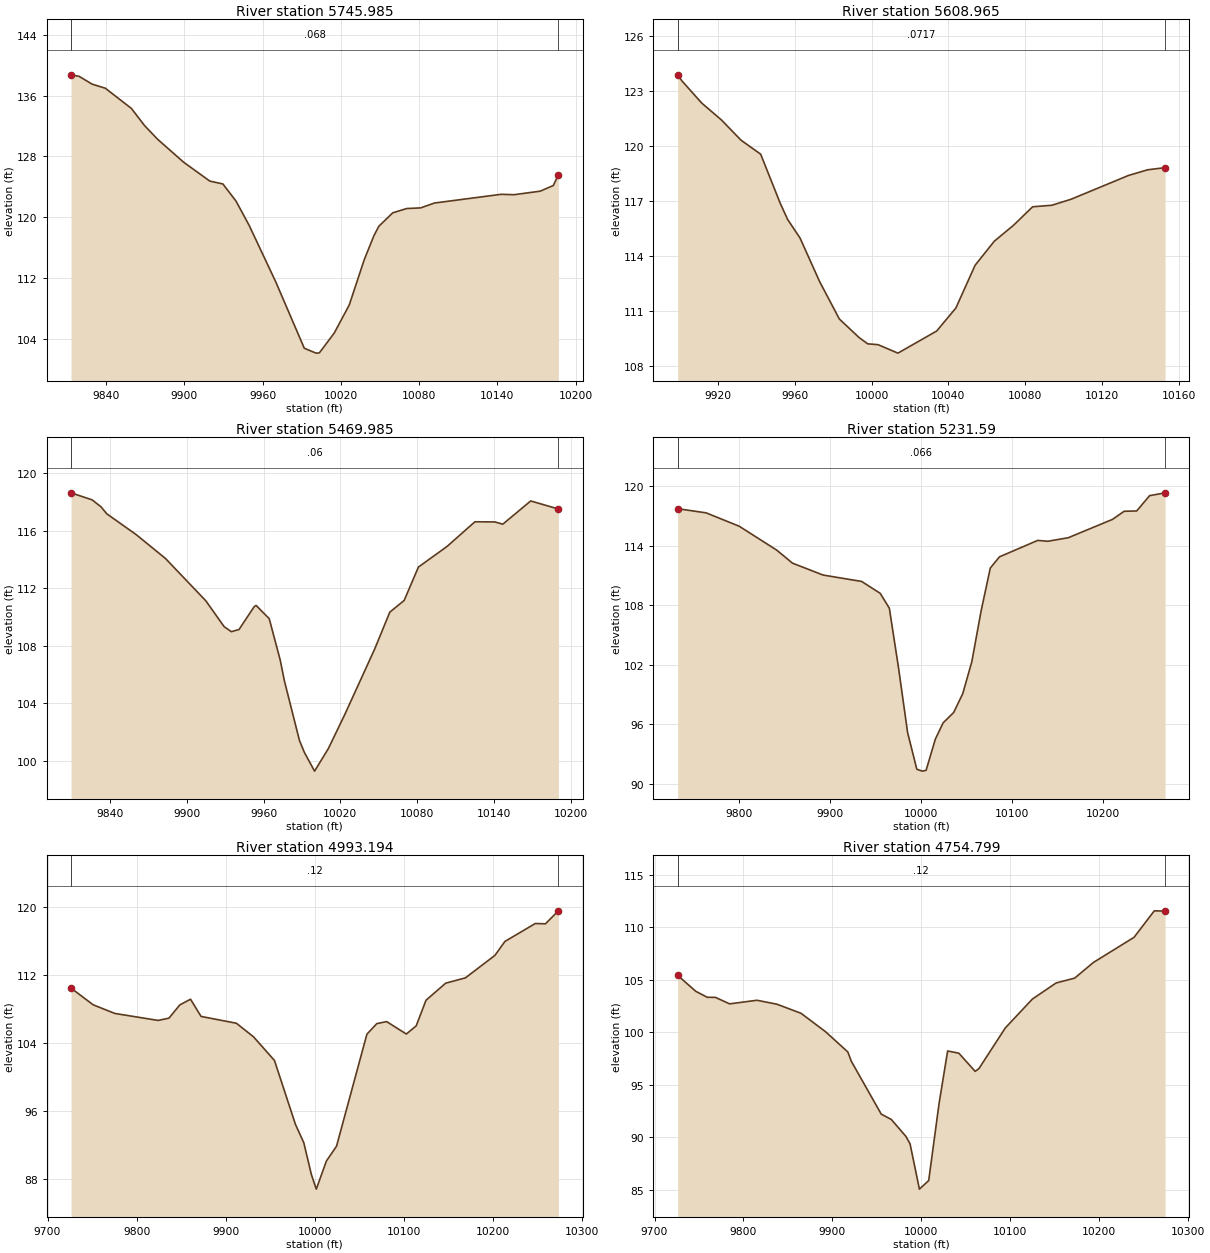
Type RM Length L Ch R = 1 ,5745.985,137.020400,137.020400,137.020400
XS GIS Cut Line= 6
999862.932179635766728.790520448999853.021897917766877.420868914
999815.977226411766951.404315447 999800.98223676766990.556784104
999789.977987805767041.965452958999787.864287347767088.895497279
#Sta/Elev= 30
9813.216138.74189819.434138.53919829.449137.50939839.464136.98179859.494134.3161
9869.508132.07019879.523130.26599899.553127.23289919.583124.74979929.597124.3734
9939.641122.12169949.714118.9254 9970.25111.43329991.993102.7428   10001102.1008
10003.53102.132310014.98104.756710026.43108.438710037.89114.378710045.22117.5131
10049.08118.799110059.78 120.57310070.49 121.138 10081.2121.223310091.74121.8625
10142.81123.010310152.82122.960510172.84123.426210182.85124.170810186.75125.5868
#Mann= 3 , 0 , 0
9813.216   0.068       09813.216   0.068       010186.75   0.068       0
#XS Ineff= 2 , 0
       0                               0
Bank Sta=9813.216,10186.75
Exp/Cntr=0.3,0.1

Type RM Length L Ch R = 1 ,5608.965,138.979600,138.979600,138.979600
XS GIS Cut Line= 4
999737.644626349766752.793105632999715.798031956766849.422273085
999710.756510168766883.032418296999709.916256577 767004.02894102
#Sta/Elev= 26
9898.909123.86859901.172123.53329911.424122.33279921.676121.41519931.929120.3112
9942.181119.54689952.434116.85879956.249115.98999962.686114.98389972.938112.6015
9983.191110.57199993.443109.56429997.977109.219210003.36109.173810013.73108.7132
10033.93109.917710043.93111.170510053.93113.494610063.93114.805910073.93115.6715
10083.93116.681910093.93116.765610103.93117.091210133.93118.389610143.93118.6981
10152.96118.8126
#Mann= 3 , 0 , 0
9898.909  0.0717       09898.909  0.0717       010152.96  0.0717       0
#XS Ineff= 2 , 0
       0                               0
Bank Sta=9898.909,10152.96
Exp/Cntr=0.3,0.1

Type RM Length L Ch R = 1 ,5469.985,238.395500,238.395500,238.395500
XS GIS Cut Line= 6
999493.547648027  766720.6269213999554.740732575766829.929524691
999589.958535183766885.912801085999621.038641172766936.387894957
999641.182224417766977.451141934999674.758486553 767054.85783971
#Sta/Elev= 30
 9809.59118.64129826.062118.15249833.034 117.6669837.523117.18199860.444115.7372
9883.365114.07429914.917111.12669929.207109.32819934.856108.97949940.839109.1299
9952.639 110.7159954.184110.80629964.438109.88659973.023107.00769976.238105.5797
9988.037101.41899991.863100.58449999.87599.2763510010.62100.842510023.42103.2053
 10046.9107.785210058.65110.339510069.87111.152510081.01 113.47710103.28114.9028
10125.14116.626610140.74116.615510146.94116.460110168.74118.075610190.39117.5161
#Mann= 3 , 0 , 0
 9809.59    0.06       0 9809.59    0.06       010190.39    0.06       0
#XS Ineff= 2 , 0
       09852.771                       0
Bank Sta=9809.59,10190.39
Exp/Cntr=0.3,0.1

Type RM Length L Ch R = 1 , 5231.59,238.395400,238.395400,238.395400
XS GIS Cut Line= 6
999199.472071449766954.324072966999363.882346463 767049.59377655
999494.433588486767050.606139053 999565.18944097767068.564274553
999616.968283897767096.684556161  999676.9510265767150.539075324
#Sta/Elev= 30
9732.103117.75019763.458117.32979799.872115.97669841.182113.55999858.263112.2603
9891.904111.0599 9934.33110.41479954.731109.21599964.779107.71369974.818101.7365
9984.84295.17944 9994.9791.47602   10001 91.287510005.1691.3681510015.3194.50364
10023.8596.1521510035.44 97.194610045.4499.0951310055.45102.328310065.59107.4208
10075.74111.767810085.88   112.910127.86114.5531 10138.9114.465810161.36114.8207
10210.07 116.67310222.82  117.4910236.64117.521510250.85119.064410267.82119.3501
#Mann= 3 , 0 , 0
9732.103   0.066       09732.103   0.066       010267.82   0.066       0
#XS Ineff= 2 , 0
       0                               0
Bank Sta=9732.103,10267.82
Exp/Cntr=0.3,0.1

Type RM Length L Ch R = 1 ,4993.194,238.395500,238.395500,238.395500
XS GIS Cut Line= 6
999124.586516103767091.526651173999232.472460937767166.211575352
999350.154507371767239.491058626999406.526814197767269.993676183
999540.242417937767332.964862057999597.792244752767364.229424035
#Sta/Elev= 30
9726.372110.4667  9751.2108.50489775.524107.49069824.174106.66959836.336 106.937
9848.498108.49149860.564109.16219872.344107.14079912.049106.33779931.245 104.747
9954.806101.96149978.36694.448999987.72392.301519996.21988.5722910001.7386.84776
 10013.190.1512410024.47 91.891710058.58105.053310069.68106.290510080.73106.5335
10102.84105.070810113.89106.025310124.95109.043510147.05 111.04810169.16111.6693
10202.32114.312310213.53115.950810247.67 118.05810259.05118.020910273.61119.5469
#Mann= 3 , 0 , 0
9726.372    0.12       09726.372    0.12       010273.61    0.12       0
#XS Ineff= 2 , 0
       0                               0
Bank Sta=9726.372,10273.61
Exp/Cntr=0.3,0.1

Type RM Length L Ch R = 1 ,4754.799,238.395400,238.395400,238.395400
XS GIS Cut Line= 6
999098.995225354767228.536126106999249.188946394767362.344334903
999269.699549668767394.331834091999294.669781895767465.995359161
999318.225820385767496.133561414999485.605275069 767593.77117845
#Sta/Elev= 30
9726.037105.43549746.517103.91579759.312103.35399768.455103.3453 9784.45102.7261
  9815.2103.06949837.599102.6939 9864.71101.82929892.169100.08279917.34898.14497
9921.33297.247119954.88992.226479966.24191.713289982.58690.108929987.28489.39761
9997.80685.0807910008.2685.90015 10019.993.2320510029.5498.2390510042.1198.02934
10060.5196.2971810064.68 96.5568 10094.4100.435310124.84103.185810151.47104.7165
10172.31105.175910193.48106.673710239.07109.062110261.86111.587610273.95111.5659
#Mann= 3 , 0 , 0
9726.037    0.12       09726.037    0.12       010273.95    0.12       0
#XS Ineff= 2 , 0
       0                               0
Bank Sta=9726.037,10273.95
Exp/Cntr=0.3,0.1

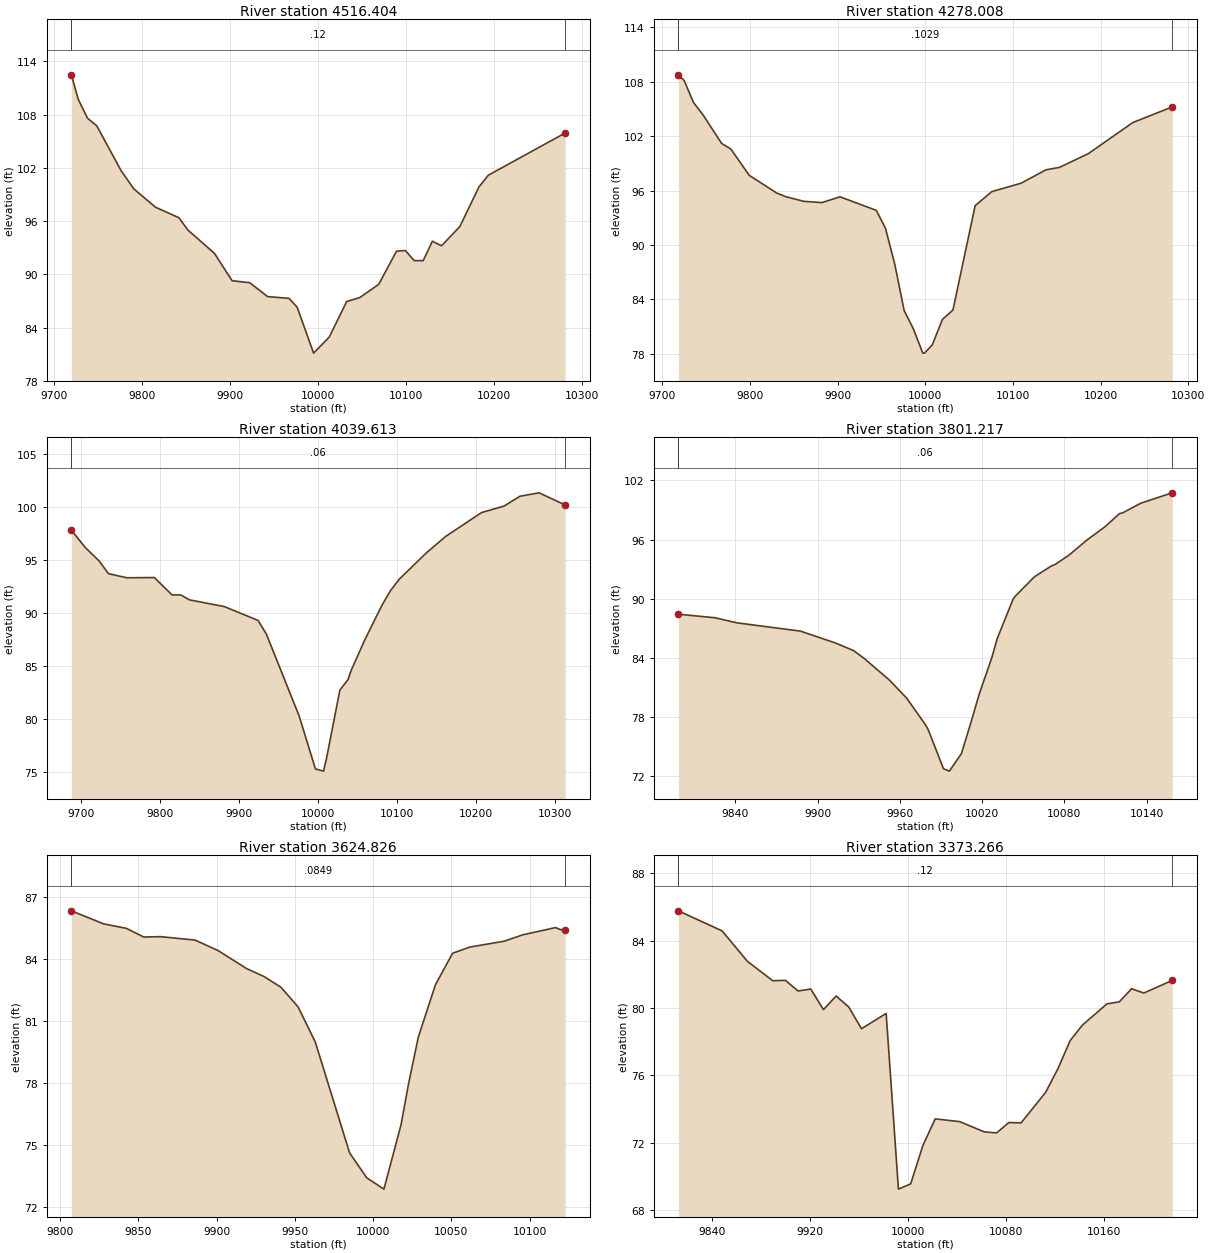
Type RM Length L Ch R = 1 ,4516.404,238.395500,238.395500,238.395500
XS GIS Cut Line= 6
998897.528600325767547.454631194999109.892647736767585.439564576
999145.740310802767569.161106753999183.633691525767512.453057012
 999215.97006407767503.397772788999404.201233077767569.417652047
#Sta/Elev= 30
9719.466112.48149727.329109.70869737.854107.58789748.379106.73089775.727101.7232
9790.42999.628159814.97497.565079841.71396.370879851.78994.995079882.01792.36047
9902.09989.27529 9922.1389.053029942.39987.485989966.847 87.2855 9976.0686.28121
9994.67281.1123610012.4782.9222210032.3286.9313910047.05 87.369810068.6988.86528
10088.8492.5976110098.9392.6758810109.0291.5362210119.2291.5369910129.6293.73187
10140.0193.2084210160.8595.3763910182.4299.82419 10193.2101.166410280.48105.9203
#Mann= 3 , 0 , 0
9719.466    0.12       09719.466    0.12       010280.48    0.12       0
#XS Ineff= 2 , 0
       0                               0
Bank Sta=9719.466,10280.48
Exp/Cntr=0.3,0.1

Type RM Length L Ch R = 1 ,4278.008,238.395400,238.395400,238.395400
XS GIS Cut Line= 6
998868.804443419767588.428619995998962.371722559767620.750289554
 999090.86909892767654.684870346999148.431837272767676.319549041
999173.198293798 767692.75040822999360.942837626767842.674817001
#Sta/Elev= 30
9718.225108.76279724.834108.12299735.502 105.699 9746.17104.37049767.506101.1991
9778.032100.58769799.01897.682289830.30795.73149 9840.6595.330569861.33694.80997
9882.02194.673799902.70795.309259944.07893.813749954.54191.833239965.17487.86893
9975.80682.783899986.43980.726169997.07278.08251    999978.0726610007.9178.97571
10019.5581.7958410031.5582.8288510056.8594.3274210075.8295.8805510109.2696.80881
10137.7398.2878810153.2198.5597610186.09100.074610236.68103.491510281.74105.2231
#Mann= 3 , 0 , 0
9718.225  0.1029       09718.225  0.1029       010281.74  0.1029       0
#XS Ineff= 2 , 0
       0                               0
Bank Sta=9718.225,10281.74
Exp/Cntr=0.3,0.1

Type RM Length L Ch R = 1 ,4039.613,238.395500,238.395500,238.395500
XS GIS Cut Line= 6
998754.593010182767755.986454964998916.271424021767844.552442973
999078.662452121767892.833066541999129.229944201767913.488003877
999215.407207427767962.432264707999312.186821988768028.813876677
#Sta/Elev= 30
9687.371 97.82479705.04996.183639722.71794.906859734.34193.71872 9757.5993.33116
9792.46393.353129814.81291.714349825.93991.708899837.067 91.24339881.16690.60926
9923.78889.301459934.44387.992489975.80980.279749996.40375.2831110006.7275.07275
10010.5576.2998410027.3982.7292910037.7383.7184510041.5184.5553710059.1687.50248
10080.7690.7500810091.57  92.12110102.6593.2018610136.5395.6573210161.42 97.2371
10206.9199.4927910235.18100.097810255.42101.029610279.67101.352410312.64100.2055
#Mann= 3 , 0 , 0
9687.371    0.06       09687.371    0.06       010312.64    0.06       0
#XS Ineff= 2 , 0
       0                               0
Bank Sta=9687.371,10312.64
Exp/Cntr=0.3,0.1

Type RM Length L Ch R = 1 ,3801.217,176.390900,176.390900,176.390900
XS GIS Cut Line= 2
998797.616485626767927.202193037999029.749447763768202.551398158
#Sta/Elev= 30
9798.51488.443739825.48488.079339840.99987.571479887.54286.72953 9913.3585.51087
9926.42984.743199934.08683.952739952.58881.743399965.11579.914929978.74777.22891
9980.62976.765249991.82772.783089996.14472.5344110004.9174.3080210011.6677.36342
10017.9980.3728210027.1784.0683910031.07 85.982110042.6989.9866610044.1490.26189
 10058.292.24199 10070.393.3119810073.7293.5264910083.3894.4334510096.4695.96236
10109.5497.2986110120.2698.6447410122.6298.72217 10135.799.6948810158.66100.7497
#Mann= 3 , 0 , 0
9798.514    0.06       09798.514    0.06       010158.66    0.06       0
#XS Ineff= 2 , 0
       0                               0
Bank Sta=9798.514,10158.66
Exp/Cntr=0.3,0.1

Type RM Length L Ch R = 1 ,3624.826,251.560000,251.560000,251.560000
XS GIS Cut Line= 2
998686.489003718767972.887935594998816.137732625768260.584638685
#Sta/Elev= 26
9807.12186.350839827.83685.715999842.34385.499529853.31285.08225 9864.28 85.0971
9886.21784.931029900.855 84.42439919.12383.548619930.09183.16978 9941.0682.64549
9952.02881.689839962.99779.989449984.93474.610229995.90273.3996110006.8772.85106
10017.8475.9841710022.5577.9363710028.8180.2119910039.7882.7605910050.7484.29315
10061.7184.5916510083.6584.8762710095.5785.1865710116.5685.5378810119.9185.43465
10122.6885.44268
#Mann= 3 , 0 , 0
9807.121  0.0849       09807.121  0.0849       010122.68  0.0849       0
#XS Ineff= 2 , 0
       0                               0
Bank Sta=9807.121,10122.68
Exp/Cntr=0.3,0.1

Type RM Length L Ch R = 1 ,3373.266,193.571300,193.571300,193.571300
XS GIS Cut Line= 3
998360.515056849768207.490397349998508.685032725768247.002390906
998758.104492068768264.288888082
#Sta/Elev= 30
9812.58485.781469848.27484.588629868.97382.779979889.67281.626629900.02181.64939
 9910.3781.01745 9920.7281.132899931.06979.908859941.41980.720389951.76880.06231
9962.11878.773929982.28679.68237 9992.3169.2413810002.3369.5549910012.3671.84511
10022.3873.4169210042.4373.2510410062.4872.64374 10072.572.5812110082.5373.19928
10092.5573.18087 10112.674.9969210122.6276.3998810132.6578.0765710142.6778.99554
10162.7280.2553110172.7480.3696110182.7781.1517510192.7980.8956610215.9581.64478
#Mann= 3 , 0 , 0
9812.584    0.12       09812.584    0.12       010215.95    0.12       0
#XS Ineff= 2 , 0
       0                10189.05       0
Bank Sta=9812.584,10215.95
Exp/Cntr=0.3,0.1