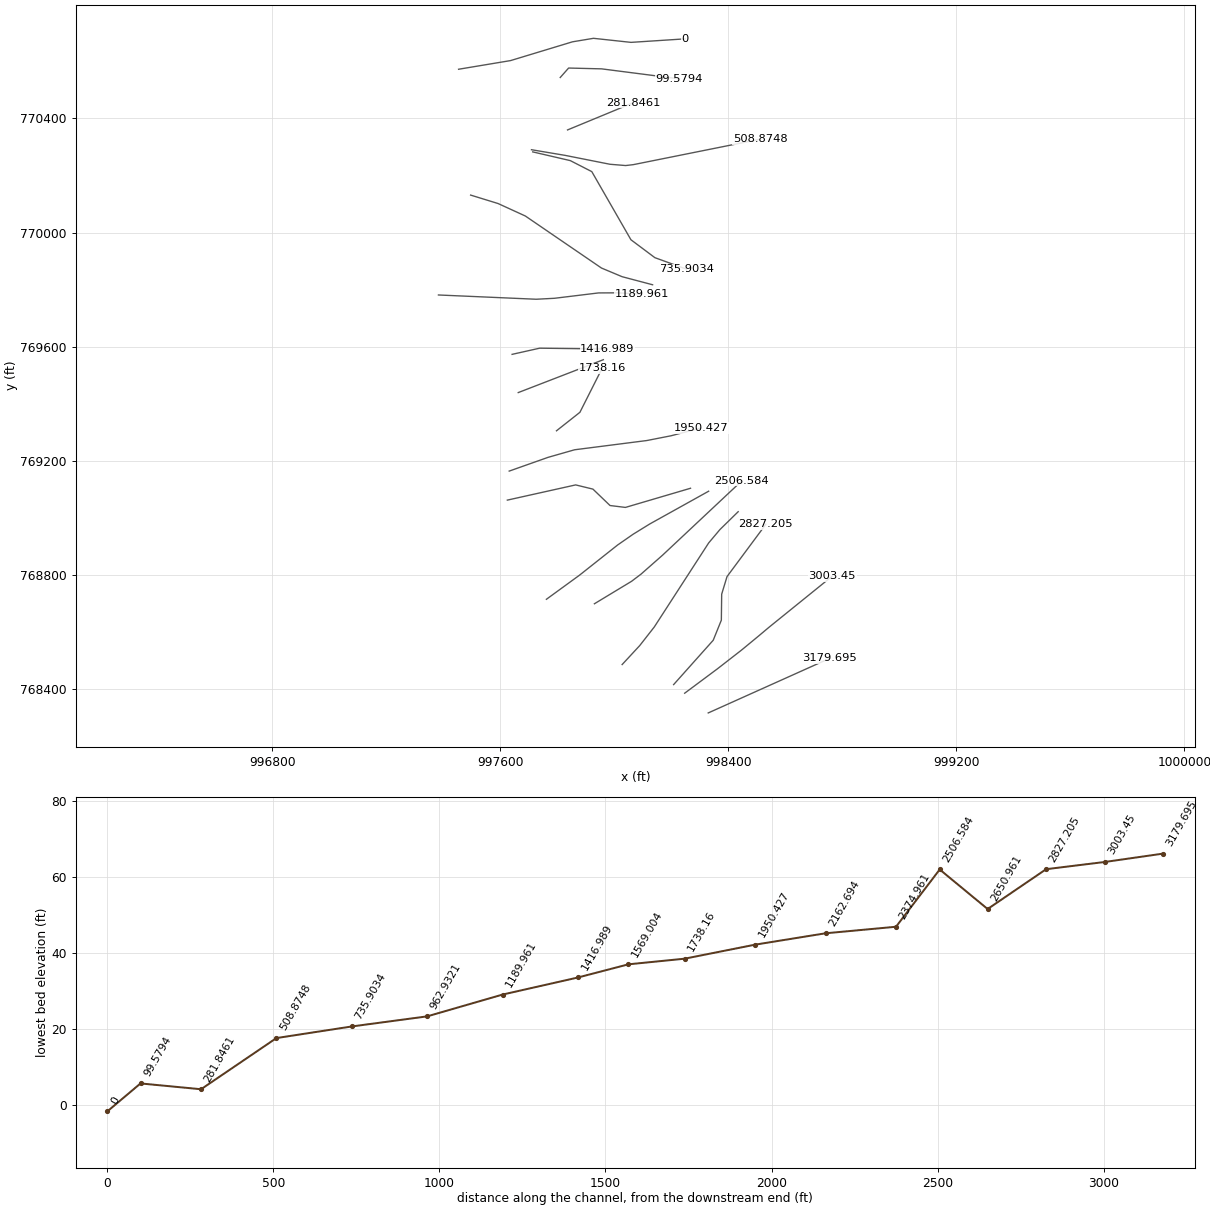
HEC-RAS study 160_ras.prj: 160

--- 160_ras.g01 (geometry) --- (continued)

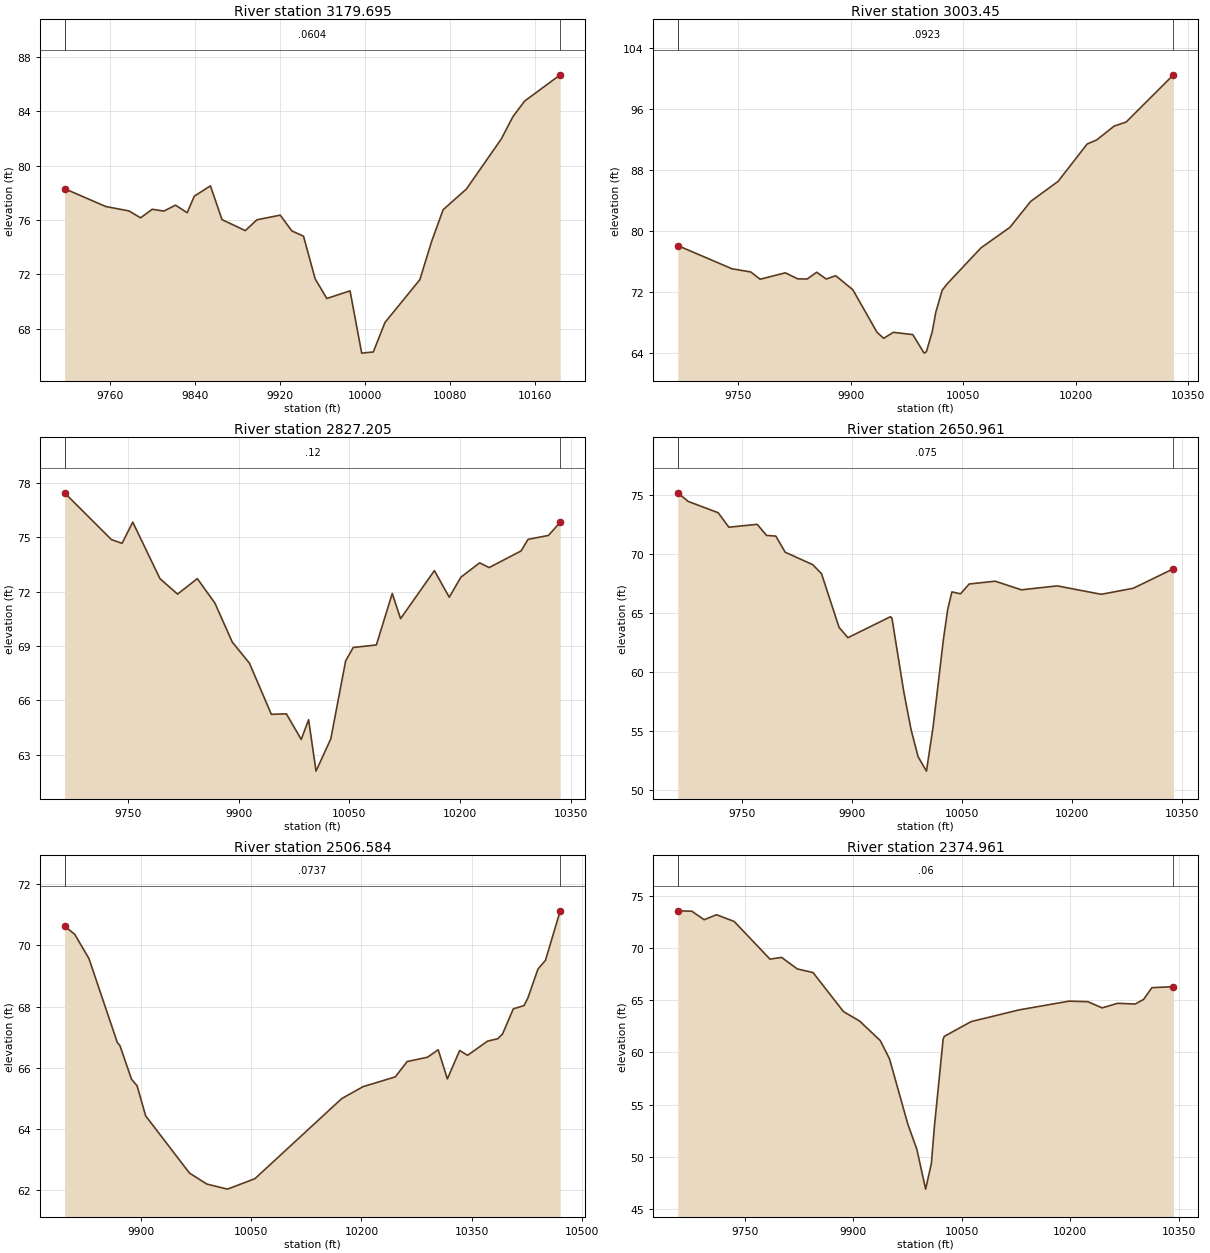
Type RM Length L Ch R = 1 ,3179.695,176.244700,176.244700,176.244700
XS GIS Cut Line= 2
998329.646311909768314.913629845 998755.63499248768506.299848646
#Sta/Elev= 30
9716.84678.301879755.60476.990079777.529 76.66479788.492 76.15699799.455 76.7858
9810.41876.650889821.38177.088829832.34476.536249839.06377.748549854.26978.50717
9865.23276.021769887.15875.219569898.12176.014699920.04776.35495 9931.0175.19318
9941.97374.809379952.93571.676649963.89870.227399985.82470.788519996.787 66.2106
10007.7566.2968210018.7168.46097 10051.671.6121410062.5674.3948810073.5376.75302
10095.4578.2730810128.3481.95866 10139.383.5958210150.2784.7373610183.8586.67012
#Mann= 3 , 0 , 0
9716.846  0.0604       09716.846  0.0604       010183.85  0.0604       0
#XS Ineff= 2 , 0
       0                10031.47       0
Bank Sta=9716.846,10183.85
Exp/Cntr=0.3,0.1

Type RM Length L Ch R = 1 , 3003.45,176.244800,176.244800,176.244800
XS GIS Cut Line= 6
998247.020556589768384.113289199998362.001129174768469.741815526
 998446.47514184768535.418792447998507.406448035768585.649701543
998542.619002927768615.279110666998764.499194503768794.654889766
#Sta/Elev= 30
9669.66978.10859 9741.9675.065389766.897   74.659779.36673.695369813.03274.53389
9829.49773.746819842.16473.727299854.83174.612119867.49773.724259880.16474.16033
9903.05972.309159935.09666.750879944.04165.943639957.00166.728489982.92166.42703
9997.97963.99908   1000164.1766510008.9566.8617710013.4969.3361710022.0172.23802
10029.0473.12222 10073.877.8136110112.3880.5089210140.0183.9078810176.6786.54318
10215.2591.4346110228.1191.9781610251.3693.7927410267.2694.3219710330.34100.5167
#Mann= 3 , 0 , 0
9669.669  0.0923       09669.669  0.0923       010330.34  0.0923       0
#XS Ineff= 2 , 0
       0                               0
Bank Sta=9669.669,10330.34
Exp/Cntr=0.3,0.1

Type RM Length L Ch R = 1 ,2827.205,176.244700,176.244700,176.244700
XS GIS Cut Line= 6
998208.254742606 768414.30398248 998347.14321023768569.892987757
 998375.63616128768640.314588312998376.810930392768731.515395988
998395.528816497768793.087067509998531.673304044768976.493070502
#Sta/Elev= 30
9664.38477.448159727.86774.869519742.252 74.66369756.71175.834059793.573 72.7176
9817.41771.86359 9844.1672.718319867.98971.369229891.48469.221089914.764  68.056
9944.43865.237799964.79665.261799984.87663.852399994.893 64.939310004.9262.10478
10024.9563.8862710045.0668.1879210055.3168.9215510086.6569.0610610108.1771.90022
10119.46 70.510710165.2273.1602610185.3771.6933610201.1672.7981610226.5173.58716
10239.3573.3269910282.5974.2428310292.0574.8820110319.7375.0998110335.6475.82736
#Mann= 3 , 0 , 0
9664.384    0.12       09664.384    0.12       010335.64    0.12       0
#XS Ineff= 2 , 0
       0                               0
Bank Sta=9664.384,10335.64
Exp/Cntr=0.3,0.1

Type RM Length L Ch R = 1 ,2650.961,144.376500,144.376500,144.376500
XS GIS Cut Line= 6
998027.700794799768484.622420657998089.306079735 768551.11582975
998140.394280797768616.392723129998331.234559204 768911.26504202
998370.930869695768958.353140885998434.688174124 769020.74693237
#Sta/Elev= 30
9662.10975.215859676.25674.486819717.15273.526899731.70472.298989770.38572.54472
9783.08371.602929795.78271.54453 9808.4870.179499845.99169.12611 9858.0168.36308
9882.04863.795399894.06762.927449952.10564.707459954.16264.564089970.131 58.3787
9980.11155.139229989.755 52.829110001.1351.6074510010.2655.3883510024.0662.67886
10029.9965.2870410035.8466.8121710047.6166.6491510059.3867.48084 10094.767.72055
10130.5366.9886210179.4267.3208710239.4766.60687 10283.167.1200510337.9168.77559
#Mann= 3 , 0 , 0
9662.109   0.075       09662.109   0.075       010337.91   0.075       0
#XS Ineff= 2 , 0
       09942.704                       0
Bank Sta=9662.109,10337.91
Exp/Cntr=0.3,0.1

Type RM Length L Ch R = 1 ,2506.584,131.623500,131.623500,131.623500
XS GIS Cut Line= 5
997930.426384836768697.837911099998060.604009539768776.549963221
998093.905262321768801.778185055998169.589927882768868.380690709
998447.100368053769128.735940069
#Sta/Elev= 30
9795.56770.632849809.40970.365399828.73669.574329867.38966.826719871.02766.71948
9886.71665.624579894.39965.405169906.04264.421959965.75262.54843 9989.4762.18804
10017.5762.02347 10054.962.3657810173.0464.9851710202.2765.3790410246.1265.69765
10262.2566.1993610289.9666.3412310304.5866.58604 10317.165.6316110333.8166.56304
10344.5266.4032710371.9466.8694910385.6666.9467110392.2767.1028910406.8967.92423
 10421.568.0327810426.7968.28286 10440.569.2286610450.7369.5145310470.8171.13408
#Mann= 3 , 0 , 0
9795.567  0.0737       09795.567  0.0737       010470.81  0.0737       0
#XS Ineff= 2 , 0
       0                               0
Bank Sta=9795.567,10470.81
Exp/Cntr=0.3,0.1

Type RM Length L Ch R = 1 ,2374.961,212.267000,212.267000,212.267000
XS GIS Cut Line= 6
997762.016199941768713.554791135997878.056274548768798.035721869
998011.650220749768903.834137555998066.285831674 768941.77069879
 998124.37367278768977.616712058998331.060324072769092.611233541
#Sta/Elev= 30
9657.374 73.54479676.81973.50733 9693.8172.69388  9710.873.172649735.28172.53252
9784.75968.929149800.90969.089829822.52267.990529844.34167.643989886.303 63.9181
 9908.7763.003169937.32761.137729950.08359.388039975.44253.140579987.74350.77152
10000.0246.9373110007.9949.4160810012.1152.91225 10024.261.2711510025.7961.54332
10063.0362.95809 10129.764.0801410198.3664.9091110224.1364.8585510244.1464.26449
10265.2664.7006710289.9164.6365810301.3665.07447 10312.866.1964610342.6266.29618
#Mann= 3 , 0 , 0
9657.374    0.06       09657.374    0.06       010342.62    0.06       0
#XS Ineff= 2 , 0
       0                               0
Bank Sta=9657.374,10342.62
Exp/Cntr=0.3,0.1

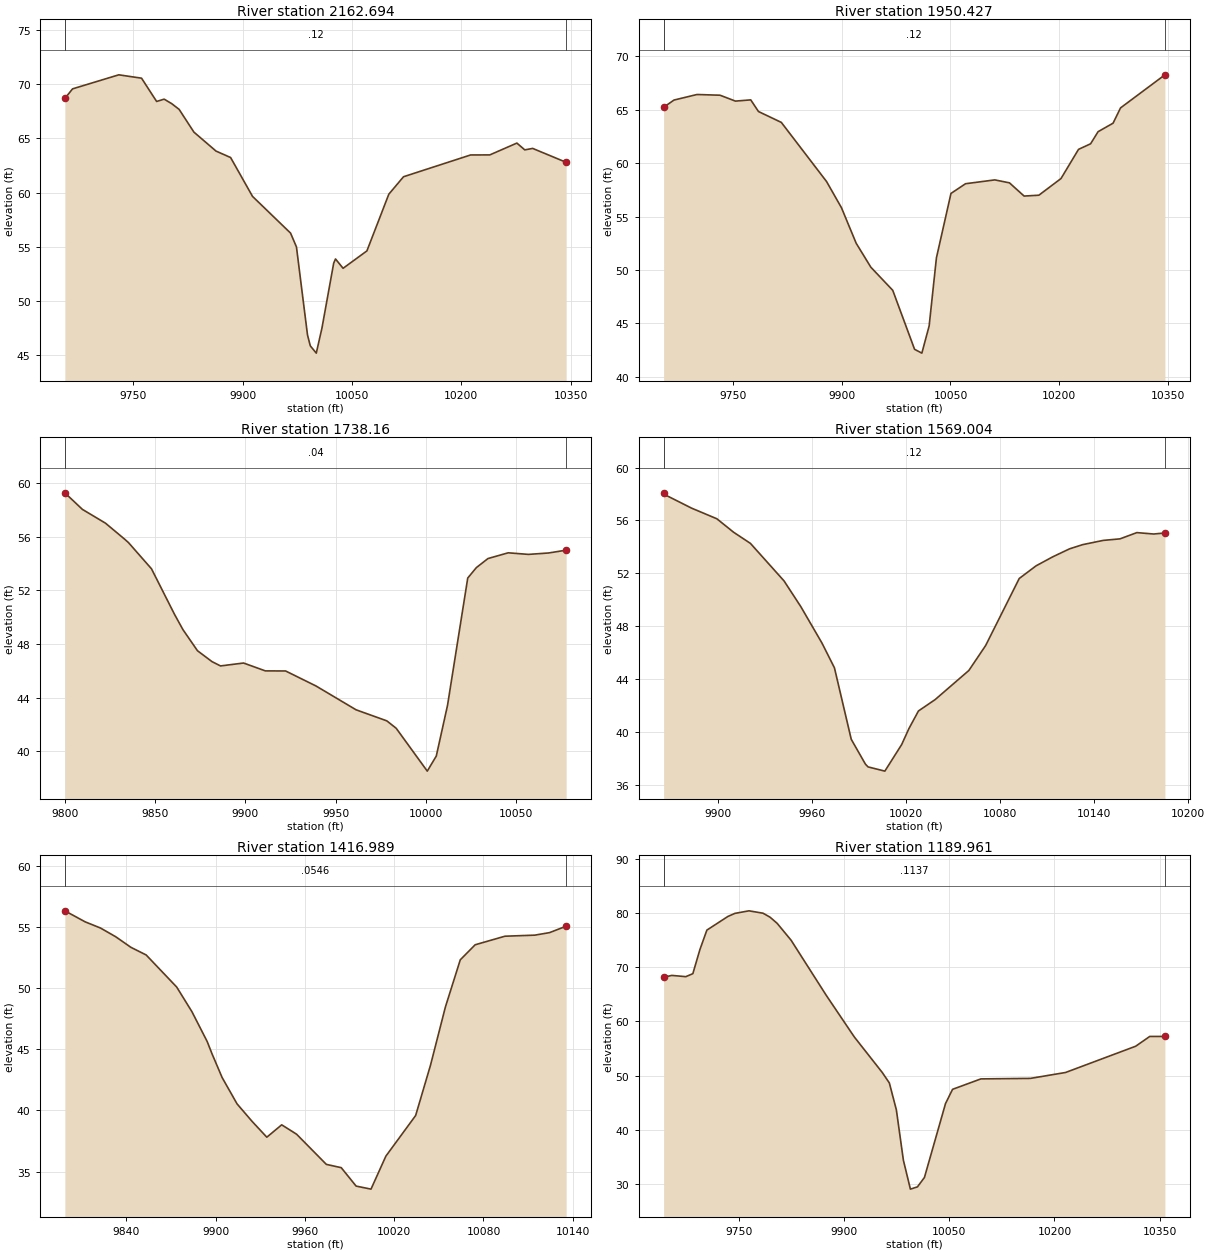
Type RM Length L Ch R = 1 ,2162.694,212.267000,212.267000,212.267000
XS GIS Cut Line= 6
997625.007921786769061.381889952997864.661167815769114.726471793
997925.241392733769099.946370607997985.152739981769042.427084276
998039.214880444769035.775428183998267.498160538769102.966875653
#Sta/Elev= 30
9656.16168.66275 9666.7269.547289730.12770.83988 9761.3470.531659782.03368.38684
9792.379    68.69802.72668.184879812.91667.655649833.17565.564439863.47663.81819
9883.48563.225059913.58159.644789965.75256.262789973.81754.990379988.96946.88428
  9992.845.88447   1000145.21323 10008.847.5253310024.8753.4932310027.3653.88507
10037.7753.0250810070.4354.6251310100.5159.8489510120.6761.45548 10212.763.46118
   1023963.4656610276.1564.5547110286.9663.9283910297.7864.0643810343.7362.78256
#Mann= 3 , 0 , 0
9656.161    0.12       09656.161    0.12       010343.73    0.12       0
#XS Ineff= 2 , 0
       0                               0
Bank Sta=9656.161,10343.73
Exp/Cntr=0.3,0.1

Type RM Length L Ch R = 1 ,1950.427,212.267000,212.267000,212.267000
XS GIS Cut Line= 6
997631.557906245769163.179158359997767.643346057 769211.31541761
997860.908439332 769237.96387758998114.211450509769270.374112356
998199.196477951 769287.06023675998304.238246712769314.461703503
#Sta/Elev= 30
9653.98765.232259668.24565.912179700.06766.434229731.88866.368159753.103 65.8168
9774.31765.930869784.92464.842669816.50963.821529878.94758.284369899.51755.83295
9919.81452.507099940.11150.258719970.30948.0961110000.4542.57155 10010.542.21456
10020.55 44.7564 10030.651.1355510050.6957.1705710070.8158.0791610111.2358.43769
10131.43 58.161410151.6556.9231910172.0357.00378 10202.6 58.565210226.7661.29617
10243.4561.8198210253.7862.9530610274.4563.7484410284.7965.1809410346.0168.27728
#Mann= 3 , 0 , 0
9653.987    0.12       09653.987    0.12       010346.01    0.12       0
#XS Ineff= 2 , 0
       0                               0
Bank Sta=9653.987,10346.01
Exp/Cntr=0.3,0.1

Type RM Length L Ch R = 1 , 1738.16,169.155500,169.155500,169.155500
XS GIS Cut Line= 3
997797.371809334769304.512088671997879.541506261769369.382902086
997957.386482358769523.631280571
#Sta/Elev= 28
9800.133 59.26289809.85258.027929822.59357.003769833.19755.811399835.33455.55553
9848.07553.601419860.81550.209759865.47449.069439873.55647.491119881.612 46.6784
9886.29746.360479899.03846.576779911.11645.990849922.31745.984519939.13444.86636
9961.32943.089469978.32442.267099983.52541.7135710000.7338.5191810005.7239.64411
10011.9343.4175510023.1352.9134210027.9253.6904310034.3354.3647510045.5354.79173
10056.7354.6740310067.9354.77953 10077.654.98965
#Mann= 3 , 0 , 0
9800.133    0.04       09800.133    0.04       0 10077.6    0.04       0
#XS Ineff= 2 , 0
       0                               0
Bank Sta=9800.133,10077.6
Exp/Cntr=0.3,0.1

Type RM Length L Ch R = 1 ,1569.004,152.014800,152.014800,152.014800
XS GIS Cut Line= 2
997663.305461645 769438.57843636997961.711203247769553.904326826
#Sta/Elev= 30
9865.16858.089489866.98557.888689882.98256.932759899.14856.127329909.86855.10546
9920.58954.263589942.031 51.42539952.75249.476389966.20246.731229974.19344.85154
9984.91439.444059993.94237.568469995.63537.3555710006.3637.0353210017.0839.04233
10021.68 40.2434 10027.841.5857110038.5242.4531510059.9644.6487710070.6846.53528
10092.1251.6077510102.8452.5642710113.5653.2514510124.2853.8539710132.6454.17078
10145.7354.4905810156.4554.6075310167.1755.0799210177.8954.9734810185.08 55.0516
#Mann= 3 , 0 , 0
9865.168    0.12       09865.168    0.12       010185.08    0.12       0
#XS Ineff= 2 , 0
       0                               0
Bank Sta=9865.168,10185.08
Exp/Cntr=0.3,0.1

Type RM Length L Ch R = 1 ,1416.989,227.028700,227.028700,227.028700
XS GIS Cut Line= 3
997641.681857139769572.644784018997738.267290443 769594.26838848
997976.126939535769591.385241225
#Sta/Elev= 30
9798.71356.299419812.36155.399939822.609 54.89749832.85654.185149843.10453.31807
9853.35152.694439873.84650.076219884.09448.062769894.341 45.6277 9897.6944.59624
9904.42342.675199914.42340.531819924.42439.114569934.42537.808999944.42638.81973
9954.42638.053259974.42835.588359984.42935.319769994.42933.8152210004.4333.56688
10014.4336.2617510034.4339.5789410044.4343.6962110054.43 48.445710064.4352.29896
10074.4453.5273610094.4454.2263210114.4454.3119810124.4454.5201710135.5755.04393
#Mann= 3 , 0 , 0
9798.713  0.0546       09798.713  0.0546       010135.57  0.0546       0
#XS Ineff= 2 , 0
       0                               0
Bank Sta=9798.713,10135.57
Exp/Cntr=0.3,0.1

Type RM Length L Ch R = 1 ,1189.961,227.028600,227.028600,227.028600
XS GIS Cut Line= 6
 997383.31961613769780.901010582997726.592768566769765.945699432
997790.436030581769769.314394732997945.016766859769788.121737807
998012.352384847769788.436060979998096.560011864769783.661522505
#Sta/Elev= 30
9642.48968.14494 9654.1868.480319674.19968.254449684.20968.801829694.21873.22554
9704.22876.838519734.25679.359449744.26679.923329764.28580.393069784.30379.95543
9794.31379.220169804.32278.102999824.341 74.97259874.38964.824729914.42757.14462
9954.465 50.56049964.47448.644979974.48443.684429984.49334.396239994.49629.06495
10004.51 29.478110014.5231.2143210044.5844.8462910054.6447.4723210095.0449.39511
10165.6649.4889110215.7950.5766810315.8655.4230610335.8957.2270210357.4957.21995
#Mann= 3 , 0 , 0
9642.489  0.1137       09642.489  0.1137       010357.49  0.1137       0
#XS Ineff= 2 , 0
       0                               0
Bank Sta=9642.489,10357.49
Exp/Cntr=0.3,0.1

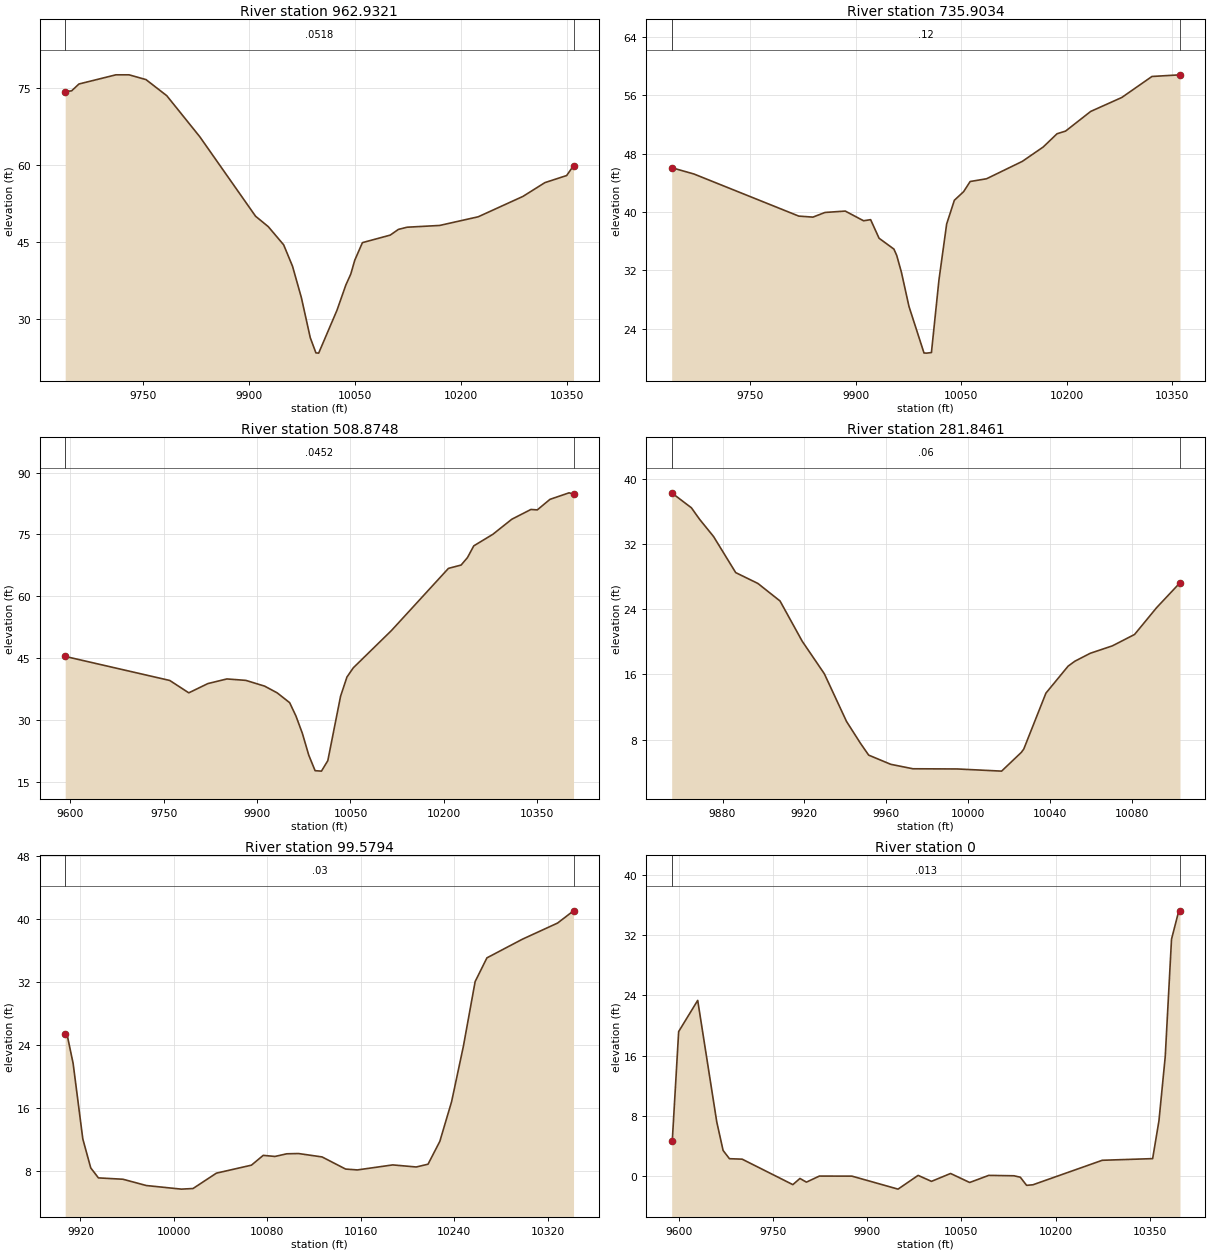
Type RM Length L Ch R = 1 ,962.9321,227.028700,227.028700,227.028700
XS GIS Cut Line= 6
 997496.25072754770131.283184065997592.314842258770101.719755895
997688.220007085 770057.85789227997955.075477352769875.440441862
998027.467716551769845.065267344998134.472163033769816.750084891
#Sta/Elev= 30
9640.43274.254899649.51174.405939659.88875.739229712.128 77.52449730.81377.52355
9754.74576.594719784.14273.456139830.72465.486369909.74749.985729927.77947.94892
9949.47944.417059962.02540.245199974.57134.120359987.11726.333729995.121 23.3742
    999923.3248710024.89 31.666110037.4836.6043310044.4438.7248510050.0741.42182
 10060.944.8435610100.2446.3088110111.7947.4211110124.1347.8474210170.1648.18896
10224.7549.8787110288.0353.8489410319.0456.5294110349.83 57.911510359.5659.83297
#Mann= 3 , 0 , 0
9640.432  0.0518       09640.432  0.0518       010359.56  0.0518       0
#XS Ineff= 2 , 0
       0                               0
Bank Sta=9640.432,10359.56
Exp/Cntr=0.3,0.1

Type RM Length L Ch R = 1 ,735.9034,227.028600,227.028600,227.028600
XS GIS Cut Line= 6
997714.030665118770282.804682549 997845.82846693770252.185597309
997921.248089749770213.569217672998058.453876941769974.645215907
998142.541709861 769911.72489865998253.515884082 769871.55348931
#Sta/Elev= 30
9638.63546.065429670.21345.205729819.39239.433829839.46739.296989856.65639.93489
9885.44840.122729911.43138.796499921.49938.946669933.49836.401769954.62134.91501
9958.66634.029529965.31231.730219976.00327.066939997.38520.68338   1000120.66396
10007.9520.7406610018.6530.69001 10029.6 38.356110040.5541.6028410053.6942.78052
10063.0244.1726510086.3544.5517310137.1646.9313310166.8748.9006810186.53 50.7149
10198.6851.0816210234.3753.7727710278.6255.6850310321.4558.5617610361.3558.78839
#Mann= 3 , 0 , 0
9638.635    0.12       09638.635    0.12       010361.35    0.12       0
#XS Ineff= 2 , 0
       0                               0
Bank Sta=9638.635,10361.35
Exp/Cntr=0.3,0.1

Type RM Length L Ch R = 1 ,508.8748,227.028700,227.028700,227.028700
XS GIS Cut Line= 6
997709.679316003770290.406759184997827.881499376770270.535029232
997984.988732425770239.383437669998040.102558201770234.889943284
998067.103874811  770238.1043083998512.002818691770327.371141716
#Sta/Elev= 30
9591.83245.412759759.72939.586039790.31336.585719820.89738.825629851.48139.95242
9881.95139.607739912.12638.209179932.16436.591619952.30534.203899962.49630.93717
9972.71826.767019982.94121.497329993.16317.7137210003.3817.60485 10013.620.14931
10034.0635.7461710044.2840.4039210054.5142.6510110115.76 51.684510207.33 66.7596
10227.6867.5670110237.8669.3742710248.0372.2196510278.5675.0116710309.12 78.6764
10339.7781.0427410349.9980.9388610370.4283.4978910401.0685.0766510408.2284.76984
#Mann= 3 , 0 , 0
9591.832  0.0452       09591.832  0.0452       010408.22  0.0452       0
#XS Ineff= 2 , 0
       0                               0
Bank Sta=9591.832,10408.22
Exp/Cntr=0.3,0.1

Type RM Length L Ch R = 1 ,281.8461,182.266700,182.266700,182.266700
XS GIS Cut Line= 2
997836.096902043 770359.80403994 998065.50544849770454.600959972
#Sta/Elev= 26
9855.17338.247639864.80636.412969868.77835.011619875.626 32.88859886.44628.46398
9897.26627.136949908.08724.985419918.90720.056669929.72716.060489940.54710.21843
9947.3327.5479859951.3676.0847299962.1874.9552929973.0074.4105169994.6484.387069
10016.294.12181910025.896.41346410027.116.82752410037.9313.6854110048.7516.99125
10052.0717.6006710059.5718.5713910070.3919.4836510081.2120.8788510092.0324.18093
 10103.427.21818
#Mann= 3 , 0 , 0
9855.173    0.06       09855.173    0.06       0 10103.4    0.06       0
#XS Ineff= 2 , 0
       0                 10065.7       0
Bank Sta=9855.173,10103.4
Exp/Cntr=0.3,0.1

Type RM Length L Ch R = 1 , 99.5794,99.579400,99.579400,99.579400
XS GIS Cut Line= 4
997810.501733601770543.710064784997839.888778836770576.888986811
997955.541021258770574.045079201998228.556150943770538.970218807
#Sta/Elev= 30
9906.92825.440979908.65125.241269913.71221.648889922.00912.035399928.7948.356861
9935.3687.0842619956.3626.9121879976.3686.11287110006.385.65459110016.385.731651
10036.397.687432 10066.4 8.7041710076.479.95010810086.569.81281710096.64 10.1501
10106.7210.1831410126.889.75146210147.05  8.207410157.138.09727510187.388.736208
10207.548.47188310217.628.82725210227.7111.7320710237.79 16.783510247.8723.82325
10257.9532.0662710268.0435.0839110298.2837.4475910328.5339.51181 10342.241.06921
#Mann= 3 , 0 , 0
9906.928    0.03       09906.928    0.03       0 10342.2    0.03       0
#XS Ineff= 2 , 0
       09911.261        10056.15       0
Bank Sta=9906.928,10342.2
Exp/Cntr=0.3,0.1

Type RM Length L Ch R = 1 ,       0,0.000000,0.000000,0.000000
XS GIS Cut Line= 6
997453.977121145770572.660049036997636.243431777770603.022418618
997853.579616696770668.909079641997927.101945251770681.165598854
998058.869664103770666.946060836998248.463504136770679.269660443
#Sta/Elev= 30
9588.8634.7308559589.8974.8011519600.00219.214019630.31623.34661 9660.637.234891
9670.734 3.445449680.8392.3524799701.0662.291924 9781.78-1.085989793.047-0.26679
9803.361-0.755929823.9880.0499899875.8170.0410099949.224-1.681619981.1880.141311
10002.44-0.6516610032.850.39275310063.27 -0.801510093.54 0.1405810133.770.088869
10143.83 -0.101310153.89-1.1819410163.95-1.1053510274.34 2.1437410354.512.362728
10364.537.35862410374.5515.8737610384.5731.4625510394.5934.7129110398.0635.22235
#Mann= 3 , 0 , 0
9588.863   0.013       09588.863   0.013       010398.06   0.013       0
#XS Ineff= 2 , 0
       09936.016           10062       0
Bank Sta=9588.863,10398.06
Exp/Cntr=0.3,0.1